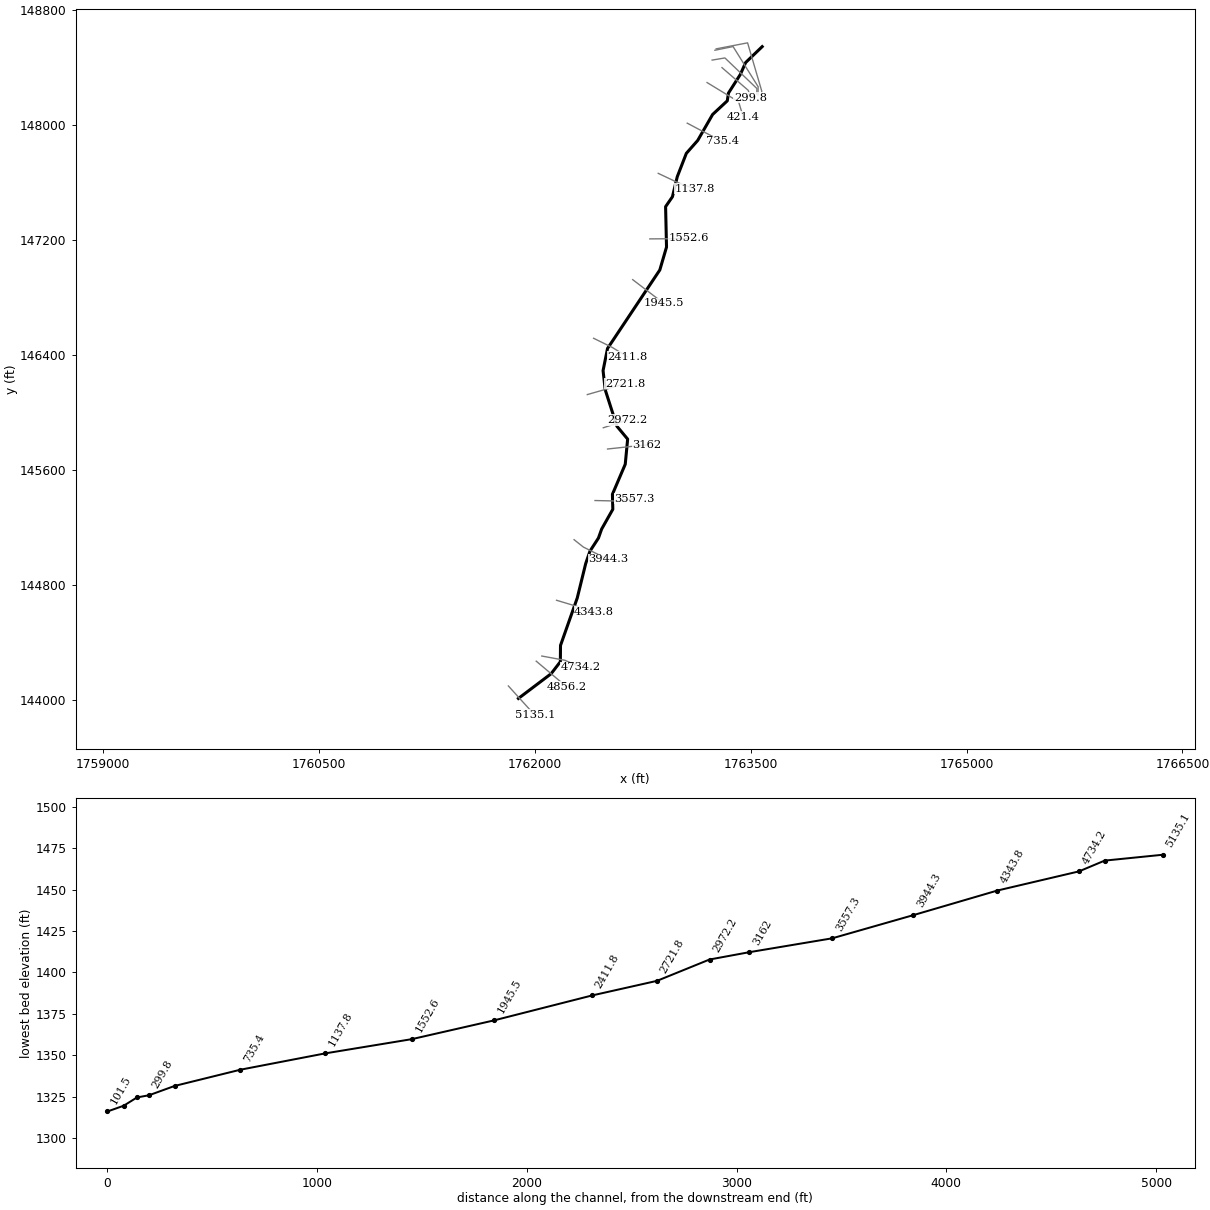
--- Crane Trace Branch.prj (project) ---

Proj Title=Crane Trace Branch
Current Plan=p01
Default Exp/Contr=0,0
English Units
Geom File=g01
Flow File=f01
Plan File=p01
BEGIN DESCRIPTION:
END DESCRIPTION:
DSS Export Rating Curves= 0
DSS Export Rating Curve Sorted= 0
DSS Export Volume Flow Curves= 0
DXF OffsetX= 0
DXF OffsetY= 0
DXF ScaleX= 0
DXF ScaleY= 0

--- Crane Trace Branch.p01 (plan) ---

Plan Title=Floodplain
Program Version=4.00
Geom File=g01
Flow File=f01
K Sum by GR=0
Std Step Tol=0.01
Critical Tol=0.01
Num of Std Step Trials=20
Max Error Tol=0.3
Flow Tol Ratio=0.001
Split Flow NTrial=30
Split Flow Tol=0.02
Split Flow Ratio=0.02
Log Output Level=0
Friction Slope Method=1
Unsteady Friction Slope Method=2
Unsteady Bridges Friction Slope Method=1
Global Log Level=0
CheckData=False
Run HTab=0
Run UNet=0
Run PostProcess=0
UNET Theta=0
UNET Theta Warmup=0
UNET ZTol=0
UNET ZSATol=0
UNET MxIter=0
UNET MaxInSteps=0
UNET DtIC=0
UNET DtMin=0
UNET MaxCRTS=0
UNET WFStab=0
UNET SFStab=0
UNET WFX=0
UNET SFX=0
UNET DSS MLevel=0
UNET DZMax Abort=0
UNET Convert EG Bridges=0
UNET Use Existing IB Tables=0
UNET Froude Limit=0
UNET Froude Power=0
Write IC File=0
Echo Input=False
Echo Output=False
Write Detailed=0

--- Crane Trace Branch.f01 (steady flow) ---

Flow Title=NFF Regression Equation
Program Version=4.00
Number of Profiles=1
Profile Names=P100yr
River Rch & RM=Crane Trace B...,Main      ,5135.1
713.8153
River Rch & RM=Crane Trace B...,Main      ,2721.8
773.0764
River Rch & RM=Crane Trace B...,Main      ,2411.8
868.5718
River Rch & RM=Crane Trace B...,Main      ,299.8
900.2421
Boundary for River Rch & Prof#=Crane Trace B...,Main      ,1
Up Type=0
Dn Type=3
Dn Slope=0.046033

--- Crane Trace Branch.g01 (geometry) ---

Geom Title=Geometry
Program Version=4.00

River Reach=Crane Trace B...,Main
Reach XY= 30
     1761886.332      144013.672     1762113.702      144185.533
      1762177.75      144268.795     1762178.817      144381.946
      1762295.17      144711.792     1762353.881      144950.904
     1762383.563      145037.401     1762442.493      145128.233
     1762464.596       145190.43     1762542.195      145327.958
     1762539.619      145432.329     1762628.603      145640.893
     1762645.298      145815.548     1762570.575      145905.214
      1762489.27      146158.852     1762474.504      146291.636
      1762505.46       146445.35     1762868.796      146990.748
     1762915.366      147149.875     1762908.961      147430.617
     1762956.491      147499.531     1762990.088      147638.772
     1763053.068      147801.027      1763132.06      147890.693
     1763235.604      148071.094      1763337.68       148166.04
     1763345.553      148219.472     1763428.476      148349.658
     1763465.108      148431.897       1763580.1      148542.569

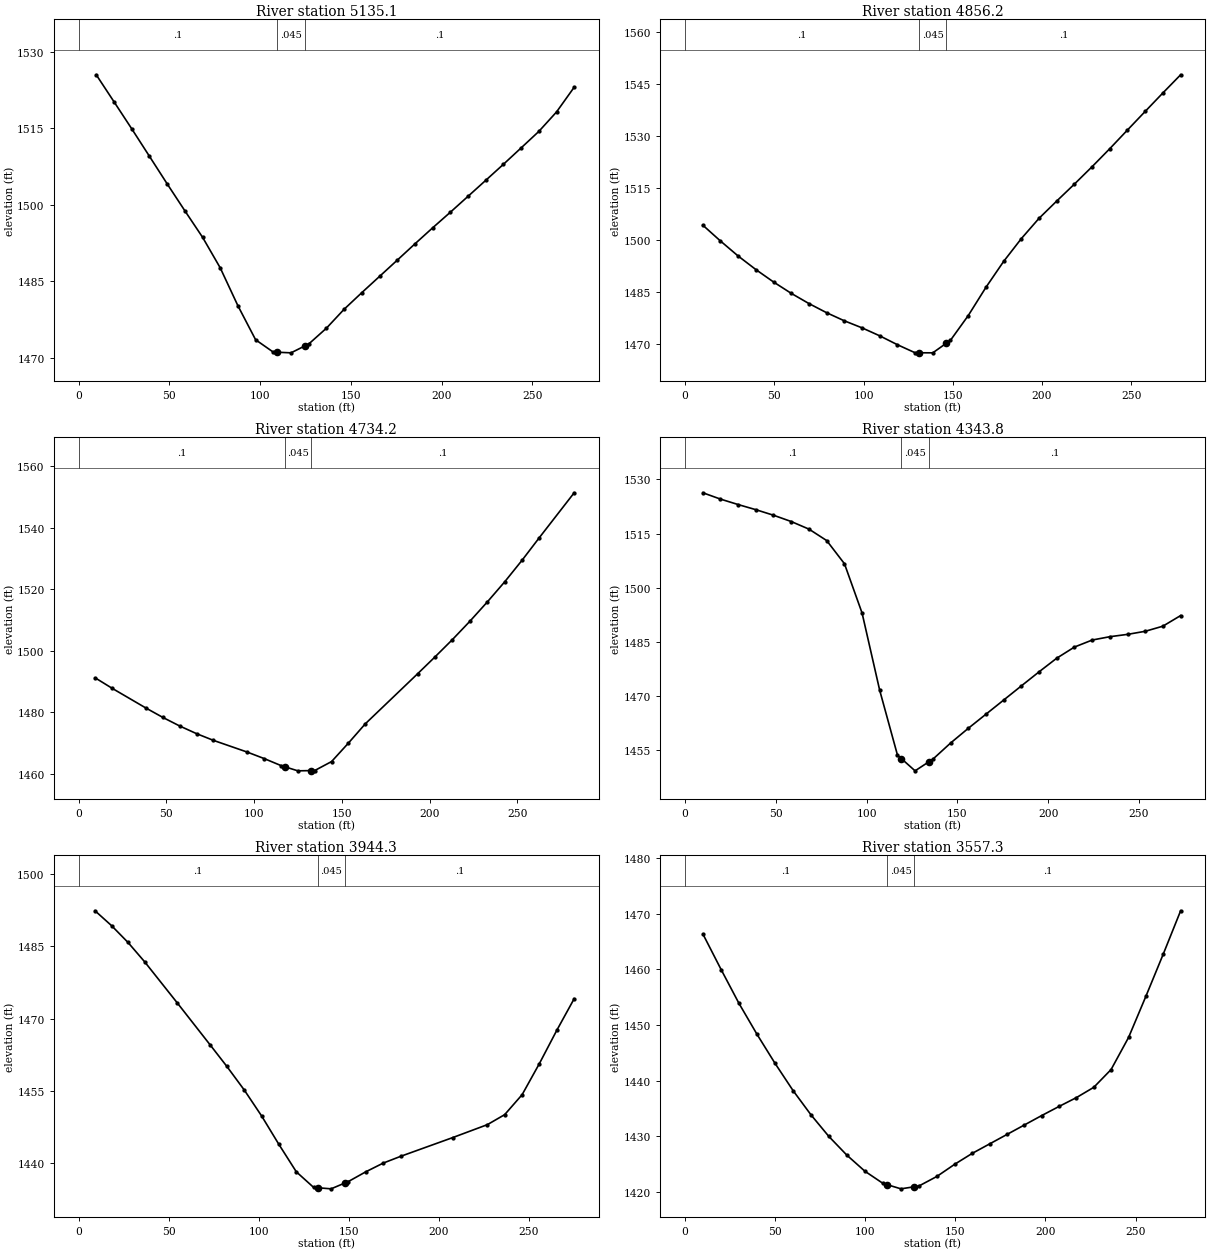
Type RM Length L Ch R = 1 ,5135.1  ,275.8,278.8,281.9
XS GIS Cut Line= 3
     1761816.553      144100.468     1761908.238      143999.344
     1761999.924       143898.22
#Sta/Elev= 30
     9.7 1525.46    19.5 1520.17    29.3 1514.86      39 1509.51    48.7 1504.15
    58.5 1498.85    68.3 1493.64      78 1487.67    87.8 1480.21    97.5 1473.59
   107.2 1471.18   109.5 1471.15     117 1471.03   124.5 1472.36   126.8 1472.77
   136.5 1475.85   146.2 1479.54     156 1482.81   165.8    1486   175.5 1489.16
   185.2 1492.34     195 1495.49   204.8 1498.56   214.5 1501.66   224.2 1504.77
     234 1507.93   243.7 1511.12   253.5 1514.36   263.3 1518.19     273 1523.02
#Mann= 3 , 0 , 0
       0      .1       0   109.5    .045       0   124.5      .1       0
Bank Sta=109.5,124.5
XS Rating Curve= 0 ,0
Exp/Cntr=0.3,0.1

Type RM Length L Ch R = 1 ,4856.2  ,110.3,122,134
XS GIS Cut Line= 2
     1762010.085      144272.762     1762222.336      144093.746
#Sta/Elev= 30
     9.9 1504.32    19.8 1499.75    29.7 1495.42    39.7 1491.48    49.6  1487.9
    59.5 1484.63    69.4 1481.69    79.3 1479.05    89.2 1476.72    99.2 1474.67
   109.1 1472.37     119 1469.81   128.9 1467.49   131.3 1467.49   138.8 1467.47
   146.3 1470.21   148.7 1471.08   158.7 1478.24   168.6 1486.38   178.5 1493.84
   188.4 1500.41   198.3 1506.26   208.2 1511.24   218.2 1516.17   228.1 1521.19
     238 1526.38   247.9 1531.76   257.8 1537.11   267.7 1542.43   277.7  1547.7
#Mann= 3 , 0 , 0
       0      .1       0   131.3    .045       0   146.3      .1       0
Bank Sta=131.3,146.3
XS Rating Curve= 0 ,0
Exp/Cntr=0.3,0.1

Type RM Length L Ch R = 1 ,4734.2  ,392.8,390.4,387.9
XS GIS Cut Line= 3
     1762048.891       144308.36     1762209.495      144278.805
     1762318.543      144231.056
#Sta/Elev= 26
     9.6 1491.17    19.2 1487.79    38.4 1481.39      48 1478.35    57.6 1475.56
    67.2 1473.07    76.8 1470.89    96.1 1467.07   105.7 1464.97   115.3 1462.69
   117.4 1462.31   124.9 1460.98   132.4 1461.06   134.5 1461.08   144.1    1464
   153.7 1470.01   163.3 1476.27   193.1 1492.55     203 1498.03   212.9 1503.65
   222.8 1509.58   232.7 1515.84   242.7 1522.45   252.6 1529.47   262.5 1536.87
   282.3 1551.43
#Mann= 3 , 0 , 0
       0      .1       0   117.4    .045       0   132.4      .1       0
Bank Sta=117.4,132.4
XS Rating Curve= 0 ,0
Exp/Cntr=0.3,0.1

Type RM Length L Ch R = 1 ,4343.8  ,403.5,399.5,395.6
XS GIS Cut Line= 3
     1762151.189      144695.821     1762281.932      144656.598
     1762412.676      144617.374
#Sta/Elev= 30
     9.8  1526.3    19.5 1524.55    29.3 1523.03      39 1521.62    48.7 1520.09
    58.5 1518.34    68.3 1516.23      78 1513.08    87.8 1506.66    97.5 1493.03
   107.2 1471.67     117 1453.72   119.2 1452.73   126.7 1449.37   134.2 1451.84
   136.5 1452.59   146.3 1457.08     156 1461.13   165.8 1465.06   175.5 1468.95
   185.2 1472.85     195 1476.76   204.7 1480.52   214.5 1483.62   224.3 1485.56
     234 1486.48   243.8 1487.13   253.5 1487.98   263.2 1489.39     273 1492.33
#Mann= 3 , 0 , 0
       0      .1       0   119.2    .045       0   134.2      .1       0
Bank Sta=119.2,134.2
XS Rating Curve= 0 ,0
Exp/Cntr=0.3,0.1

Type RM Length L Ch R = 1 ,3944.3  ,377,387,397
XS GIS Cut Line= 3
     1762273.073      145116.848     1762337.529      145065.656
      1762509.96      144979.173
#Sta/Elev= 26
     9.1 1492.43    18.3 1489.33    27.4 1485.85    36.6 1481.84    54.9  1473.2
    73.2 1464.44    82.3 1460.05      92 1455.12   101.6 1449.74   111.2 1443.82
   120.9  1438.1   130.5 1434.86   132.7 1434.79   140.2 1434.56   147.7 1435.75
   149.8 1436.08   159.5 1438.11   169.1 1439.91   178.8 1441.32   207.7 1445.22
     227 1447.92   236.6    1450   246.3 1454.16   255.9 1460.64   265.6 1467.59
   275.2 1474.13
#Mann= 3 , 0 , 0
       0      .1       0   132.7    .045       0   147.7      .1       0
Bank Sta=132.7,147.7
XS Rating Curve= 0 ,0
Exp/Cntr=0.3,0.1

Type RM Length L Ch R = 1 ,3557.3  ,392.4,395.3,398.2
XS GIS Cut Line= 3
     1762418.615      145388.888     1762568.282      145385.379
     1762692.386      145402.525
#Sta/Elev= 30
      10 1466.24      20 1459.93    29.9 1453.86    39.9 1448.31    49.9  1443.1
    59.9 1438.21    69.9 1433.83    79.8 1429.96    89.8  1426.6    99.8 1423.72
   109.8 1421.54   112.3 1421.29   119.8 1420.56   127.3 1420.94   129.7 1421.06
   139.7 1422.78   149.7 1424.99   159.3 1426.92     169 1428.63   178.6 1430.32
   188.3 1432.03   197.9 1433.72   207.5 1435.35   217.2 1436.95   226.8 1438.79
   236.4 1441.98   246.1 1447.74   255.7 1455.12   265.4 1462.75     275 1470.49
#Mann= 3 , 0 , 0
       0      .1       0   112.3    .045       0   127.3      .1       0
Bank Sta=112.3,127.3
XS Rating Curve= 0 ,0
Exp/Cntr=0.3,0.1

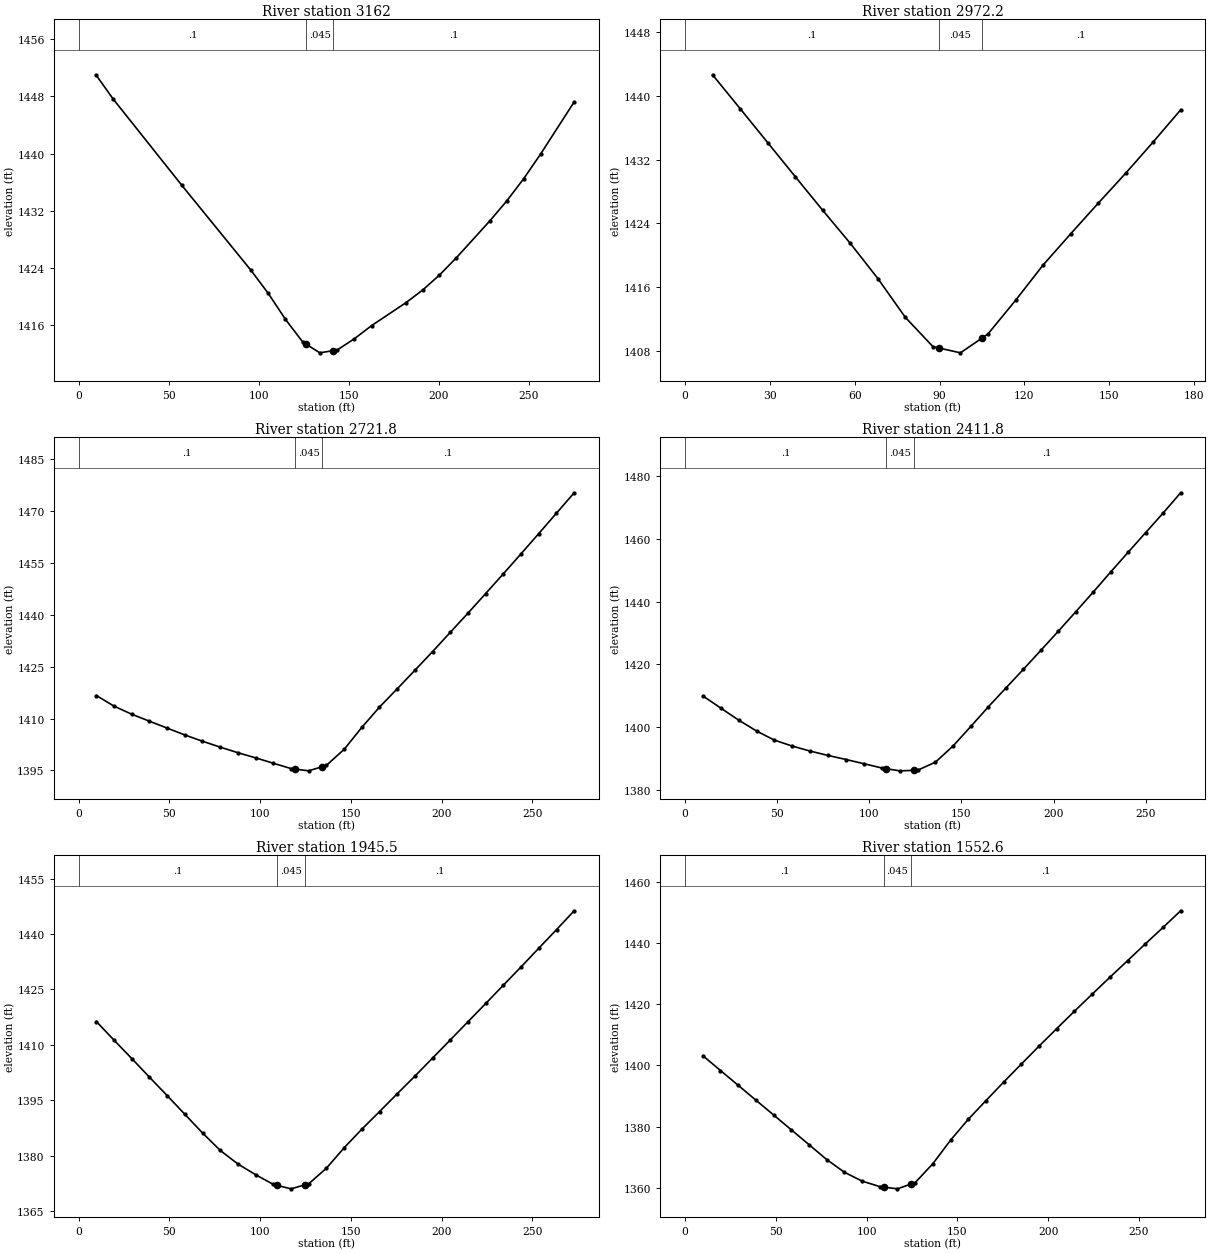
Type RM Length L Ch R = 1 ,3162    ,185,189.8,194.7
XS GIS Cut Line= 3
     1762505.707      145746.845     1762677.051      145765.315
     1762779.546      145775.225
#Sta/Elev= 22
     9.6 1451.01    19.1 1447.65    57.4 1435.55    95.7 1423.72   105.3  1420.5
   114.9 1416.86   124.5 1413.69   126.5 1413.37     134 1412.18   141.5 1412.49
   143.6 1412.57   153.2 1414.15   162.8 1415.99   181.7 1419.16   191.1 1420.94
   200.4 1423.03   209.8 1425.44   228.5 1430.62   237.9 1433.41   247.2 1436.48
   256.6 1439.92   275.3 1447.22
#Mann= 3 , 0 , 0
       0      .1       0   126.5    .045       0   141.5      .1       0
Bank Sta=126.5,141.5
XS Rating Curve= 0 ,0
Exp/Cntr=0.3,0.1

Type RM Length L Ch R = 1 ,2972.2  ,251.1,250.4,249.7
XS GIS Cut Line= 2
     1762476.131      145894.479     1762643.061      145948.108
#Sta/Elev= 20
     9.7 1442.65    19.5 1438.39    29.2 1434.14      39 1429.85    48.7 1425.63
    58.4 1421.51    68.2 1417.07    77.9 1412.21    87.7 1408.52    89.9 1408.35
    97.4 1407.75   104.9 1409.57   107.1  1410.1   116.9 1414.34   126.6 1418.75
   136.4 1422.69   146.1 1426.51   155.9 1430.31   165.6 1434.22   175.3 1438.25
#Mann= 3 , 0 , 0
       0      .1       0    89.9    .045       0   104.9      .1       0
Bank Sta=89.9,104.9
XS Rating Curve= 0 ,0
Exp/Cntr=0.3,0.1

Type RM Length L Ch R = 1 ,2721.8  ,326.7,310,293.3
XS GIS Cut Line= 3
      1762365.09      146125.013     1762496.311      146162.606
     1762627.532        146200.2
#Sta/Elev= 30
     9.8 1416.66    19.5 1413.59    29.2 1411.26      39 1409.24    48.8 1407.23
    58.5 1405.25    68.2 1403.44      78 1401.73    87.7 1400.12    97.5 1398.63
   107.3 1397.06     117 1395.53   119.2 1395.38   126.7 1394.87   134.2 1396.08
   136.5 1396.46   146.3  1401.1     156 1407.43   165.7 1413.29   175.5  1418.6
   185.2 1423.94     195 1429.38   204.7 1434.92   214.5  1440.5   224.2 1446.15
     234 1451.89   243.8 1457.71   253.5 1463.53   263.2  1469.4     273 1475.33
#Mann= 3 , 0 , 0
       0      .1       0   119.2    .045       0   134.2      .1       0
Bank Sta=119.2,134.2
XS Rating Curve= 0 ,0
Exp/Cntr=0.3,0.1

Type RM Length L Ch R = 1 ,2411.8  ,470.7,466.3,461.9
XS GIS Cut Line= 3
     1762408.905      146516.124     1762539.579       146451.92
     1762644.613      146387.094
#Sta/Elev= 30
     9.7 1409.93    19.4 1406.06    29.1 1402.22    38.8 1398.75    48.5 1395.83
    58.2 1393.94    67.9 1392.34    77.7 1390.94    87.4 1389.65    97.1 1388.31
   106.8 1386.95     109 1386.74   116.5 1386.04     124 1386.19   126.2 1386.23
   135.9 1388.81   145.6 1394.05   155.1 1400.21   164.6 1406.46   174.1 1412.45
   183.6 1418.42   193.1 1424.48   202.6  1430.6   212.1 1436.83   221.6 1443.12
     231 1449.48   240.5  1455.8     250 1462.06   259.5 1468.32     269 1474.78
#Mann= 3 , 0 , 0
       0      .1       0     109    .045       0     124      .1       0
Bank Sta=109,124
XS Rating Curve= 0 ,0
Exp/Cntr=0.3,0.1

Type RM Length L Ch R = 1 ,1945.5  ,378,392.9,407.8
XS GIS Cut Line= 3
     1762680.315      146923.696     1762788.745      146840.779
     1762897.175      146757.862
#Sta/Elev= 30
     9.8  1416.3    19.5 1411.27    29.3 1406.28      39 1401.26    48.8 1396.24
    58.5 1391.21    68.3 1386.12      78 1381.43    87.7 1377.76    97.5 1374.85
   107.3 1372.21   109.5 1371.94     117 1371.02   124.5 1372.08   126.8 1372.41
   136.5  1376.6   146.3 1382.15     156 1387.16   165.8 1391.94   175.5 1396.75
   185.3 1401.55     195 1406.42   204.8 1411.35   214.5 1416.26   224.3  1421.2
     234 1426.15   243.8 1431.13   253.5 1436.16   263.3  1441.2     273 1446.29
#Mann= 3 , 0 , 0
       0      .1       0   109.5    .045       0   124.5      .1       0
Bank Sta=109.5,124.5
XS Rating Curve= 0 ,0
Exp/Cntr=0.3,0.1

Type RM Length L Ch R = 1 ,1552.6  ,425.1,414.8,404.8
XS GIS Cut Line= 3
      1762799.22      147206.725     1762935.718       147207.77
     1763072.206      147209.551
#Sta/Elev= 30
     9.8 1403.18    19.5 1398.34    29.3 1393.49      39 1388.65    48.8  1383.8
    58.5 1378.97    68.3  1374.1      78 1369.25    87.8 1365.08    97.5  1362.2
   107.3  1360.4   109.5 1360.23     117 1359.67   124.5 1361.26   126.8 1361.74
   136.5 1367.89   146.3 1375.61     156  1382.4   165.8 1388.54   175.5 1394.56
   185.3 1400.48     195 1406.32   204.8 1412.07   214.5 1417.73   224.3 1423.31
     234 1428.81   243.8 1434.26   253.5  1439.7   263.3  1445.1     273 1450.55
#Mann= 3 , 0 , 0
       0      .1       0   109.5    .045       0   124.5      .1       0
Bank Sta=109.5,124.5
XS Rating Curve= 0 ,0
Exp/Cntr=0.3,0.1

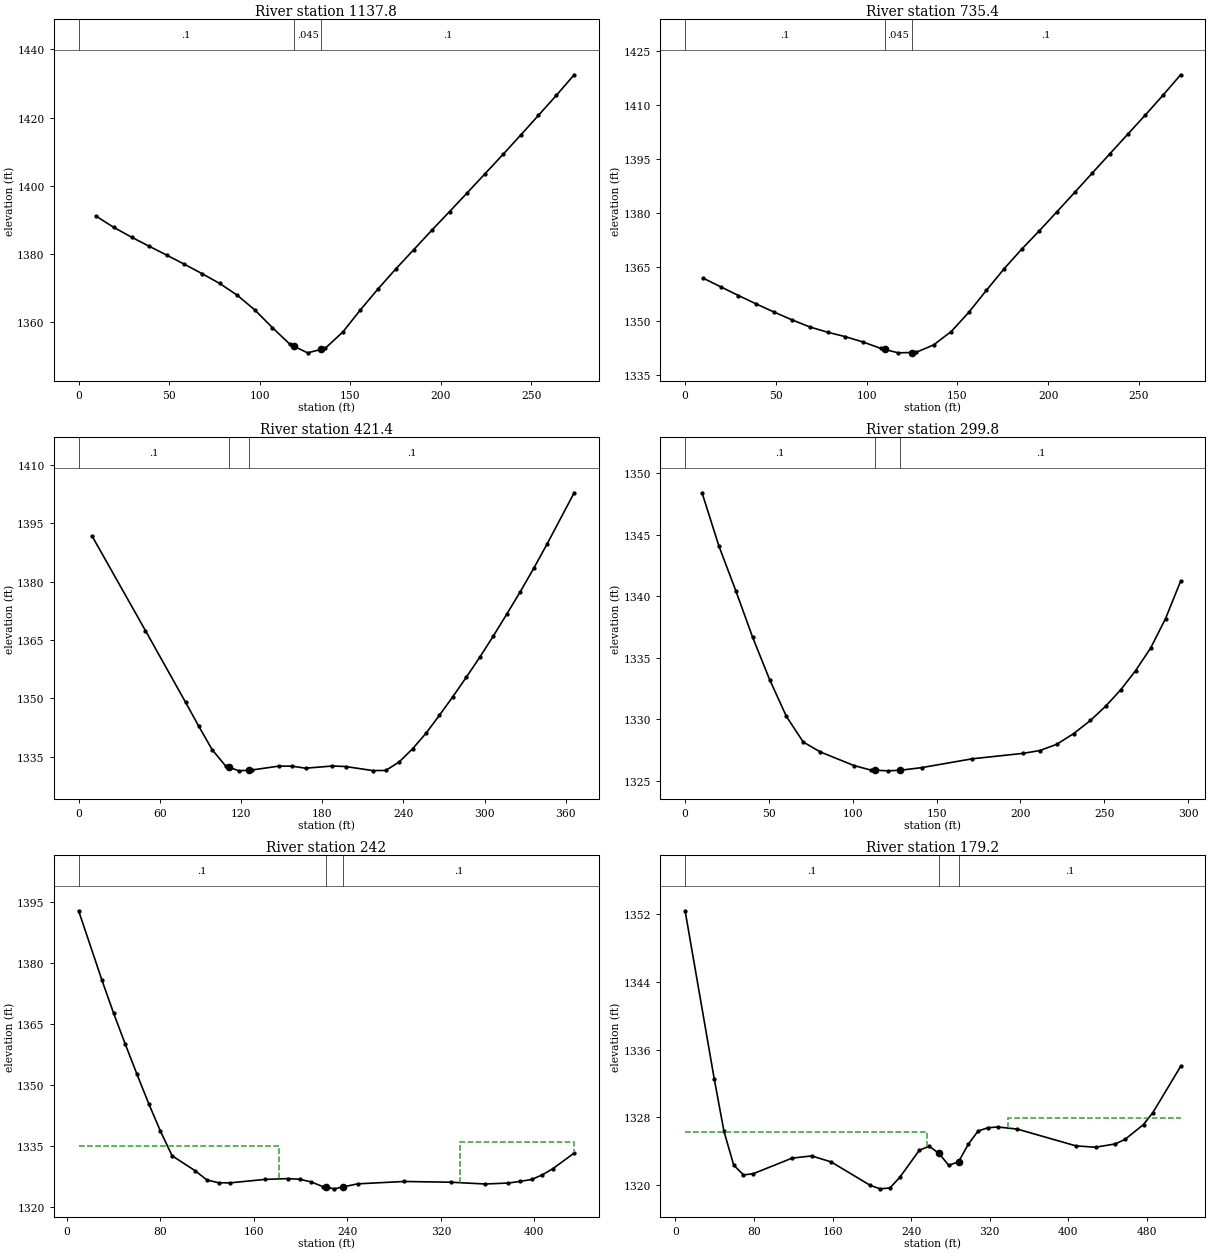
Type RM Length L Ch R = 1 ,1137.8  ,403.2,402.4,401.3
XS GIS Cut Line= 3
     1762857.831      147662.082     1762998.463      147595.547
     1763109.423      147555.318
#Sta/Elev= 30
     9.7  1391.1    19.4 1387.83    29.2 1384.96    38.9  1382.3    48.6  1379.7
    58.3 1377.04    68.1 1374.27    77.8  1371.4    87.5 1367.96    97.2 1363.65
     107 1358.42   116.7 1353.52   118.9 1352.95   126.4 1351.03   133.9 1352.04
   136.1 1352.34   145.9 1357.16   155.6 1363.64   165.4 1369.83   175.2 1375.69
   185.1 1381.33   194.9 1386.93   204.8 1392.46   214.6 1397.99   224.4 1403.57
   234.3 1409.21   244.1 1414.91   253.9 1420.69   263.8 1426.57   273.6 1432.58
#Mann= 3 , 0 , 0
       0      .1       0   118.9    .045       0   133.9      .1       0
Bank Sta=118.9,133.9
XS Rating Curve= 0 ,0
Exp/Cntr=0.3,0.1

Type RM Length L Ch R = 1 ,735.4   ,315.8,314,312.1
XS GIS Cut Line= 3
     1763059.335      148010.881     1763128.671      147974.019
     1763301.418      147884.688
#Sta/Elev= 30
     9.8 1361.99    19.6 1359.55    29.4 1357.13    39.3 1354.76    49.1 1352.52
    58.9 1350.37    68.7 1348.41    78.5 1346.94    88.2 1345.72      98 1344.23
   107.7 1342.47   109.9 1342.19   117.4 1341.22   124.9 1341.31   127.1 1341.33
   136.9 1343.41   146.6 1347.13   156.3 1352.47     166 1358.57   175.8 1364.59
   185.5 1370.03   195.2 1375.12   204.9  1380.4   214.7 1385.79   224.4 1391.16
   234.1 1396.51   243.8 1401.86   253.6 1407.25   263.3 1412.73     273 1418.39
#Mann= 3 , 0 , 0
       0      .1       0   109.9    .045       0   124.9      .1       0
Bank Sta=109.9,124.9
XS Rating Curve= 0 ,0
Exp/Cntr=0.3,0.1

Type RM Length L Ch R = 1 ,421.4   ,125,121.6,118.3
XS GIS Cut Line= 3
     1763197.138      148292.987     1763416.263      148159.374
      1763448.33      148054.622
#Sta/Elev= 30
     9.9 1391.72    49.4  1367.4      79 1349.02    88.8 1342.84    98.7 1336.82
   108.6 1332.66     111 1332.35   118.5  1331.4     126 1331.58   128.3 1331.63
   148.1 1332.62   157.9 1332.59   167.8 1332.08   187.6 1332.64   197.4 1332.51
   217.2 1331.47     227  1331.5   236.9 1333.69   246.8 1337.07   256.6 1341.01
   266.6 1345.66   276.6 1350.47   286.5 1355.45   296.5  1360.6   306.4    1366
   316.4 1371.65   326.4 1377.42   336.3 1383.41   346.3 1389.73   366.2 1402.81
#Mann= 3 , 0 , 0
       0      .1       0     111    .045       0     126      .1       0
Bank Sta=111,126
XS Rating Curve= 0 ,0
Exp/Cntr=0.3,0.1

Type RM Length L Ch R = 1 ,299.8   ,59.2,57.8,56.4
XS GIS Cut Line= 3
     1763300.822      148396.671     1763483.604      148238.473
     1763499.158      148187.014
#Sta/Elev= 26
    10.1 1348.43    20.1 1344.12    30.2 1340.47    40.3 1336.66    50.4 1333.23
    60.4 1330.23    70.5 1328.14    80.6 1327.34   100.7 1326.23   110.8 1325.86
   113.4 1325.85   120.9  1325.8   128.4 1325.85     141 1326.06   171.2 1326.78
   201.4 1327.22   211.5 1327.45   221.6 1327.96   231.7 1328.83   241.7  1329.9
   250.7 1331.05   259.7 1332.38   268.6 1333.95   277.6 1335.79   286.5 1338.19
   295.5 1341.24
#Mann= 3 , 0 , 0
       0      .1       0   113.4    .045       0   128.4      .1       0
Bank Sta=113.4,128.4
XS Rating Curve= 0 ,0
Exp/Cntr=0.3,0.1

Type RM Length L Ch R = 1 ,242     ,69.9,62.8,55.7
XS GIS Cut Line= 4
     1763232.412      148449.047     1763321.131      148464.012
     1763543.463        148251.3     1763542.394      148214.957
#Sta/Elev= 30
      10 1392.84      30 1375.73      40 1367.59      50 1359.97      60 1352.58
      70 1345.39      80 1338.64      90 1332.59   109.8 1328.89   119.7 1326.65
   129.7 1325.96   139.6 1325.93   169.4 1326.78   189.2 1326.98   199.2 1326.82
   209.1 1326.15     219    1325   221.4 1324.87   228.9 1324.46   236.4 1324.95
   248.8 1325.69   288.5 1326.27   328.2 1326.09     358 1325.65   377.8 1325.89
   387.7  1326.3   397.7 1326.76   406.8 1327.91   415.8 1329.42     434 1333.26
#Mann= 3 , 0 , 0
      10      .1       0   221.4    .045       0   236.4      .1       0
#XS Ineff= 2 , 0
          181.21 1335.06  336.41         1335.94
Permanent Ineff=
       F       F
Bank Sta=221.4,236.4
XS Rating Curve= 0 ,0
Exp/Cntr=0.3,0.1

Type RM Length L Ch R = 1 ,179.2   ,83.3,77.7,72.1
XS GIS Cut Line= 4
     1763251.652      148517.457     1763377.783      148543.111
     1763552.014      148264.127     1763550.945      148207.475
#Sta/Elev= 30
     9.9 1352.44    39.6 1332.49    49.5 1326.29    59.4  1322.3    69.3 1321.14
    79.2 1321.28   118.8 1323.13   138.7 1323.39   158.6 1322.68   198.5 1319.89
   208.5 1319.49   218.4  1319.6   228.4 1320.85   248.3 1324.06   258.3 1324.54
   268.3 1323.69   278.2 1322.28   288.2 1322.69   298.2 1324.78   308.1 1326.34
   318.1 1326.73   328.1 1326.82     348 1326.57   407.8 1324.58   427.7 1324.42
   447.7 1324.81   457.6 1325.34   476.5 1327.11     486 1328.52   514.3    1334
#Mann= 3 , 0 , 0
     9.9      .1       0   268.3    .045       0   288.2      .1       0
#XS Ineff= 2 , 0
           255.7 1326.22  338.26         1327.84
Permanent Ineff=
       F       F
Bank Sta=268.3,288.2
XS Rating Curve= 0 ,0
Exp/Cntr=0.3,0.1

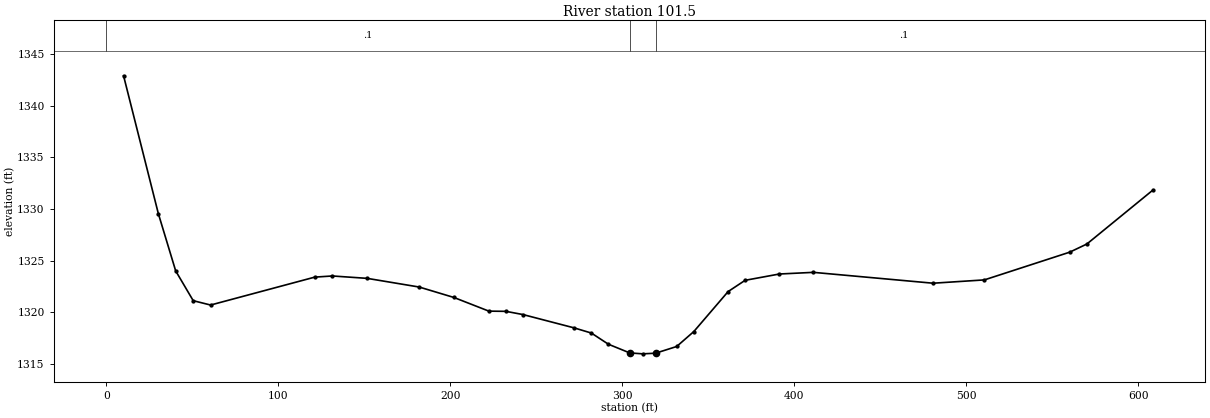
Type RM Length L Ch R = 1 ,101.5   ,85.9,101.5,117
XS GIS Cut Line= 4
     1763260.203      148527.077     1763478.705       148568.91
     1763576.599      148235.266     1763577.668      148196.786
#Sta/Elev= 30
    10.1 1342.89    30.3 1329.57    40.4 1324.02    50.6 1321.14    60.7 1320.72
   121.3 1323.42   131.5 1323.53   151.7  1323.3     182 1322.46   202.2 1321.45
   222.5 1320.13   232.4 1320.11   242.3  1319.8   272.1 1318.51   282.1 1318.01
     292 1316.93   304.4 1316.09   311.9    1316   319.4 1316.06   331.7 1316.71
   341.7 1318.16   361.6 1322.02   371.5 1323.11   391.4 1323.72   411.2 1323.88
   480.8 1322.83   510.6 1323.15   560.2 1325.83   570.2 1326.62   608.7 1331.85
#Mann= 3 , 0 , 0
       0      .1       0   304.4    .045       0   319.4      .1       0
Bank Sta=304.4,319.4
XS Rating Curve= 0 ,0
Exp/Cntr=0.3,0.1

Chan Stop Cuts=-1
Use User Specified Reach Order=0